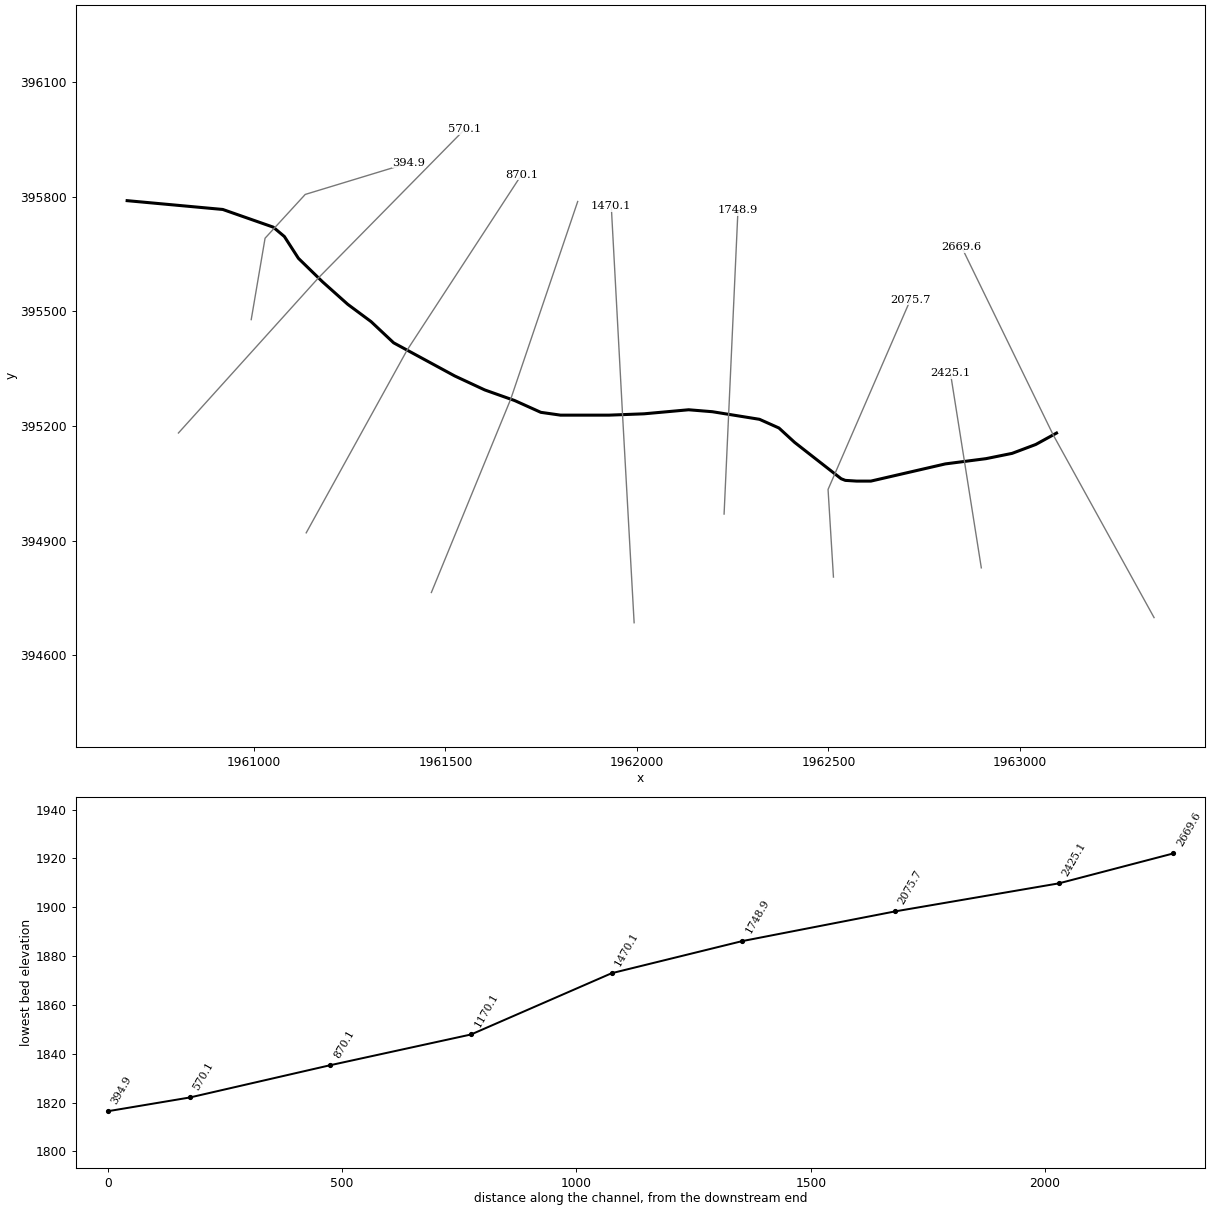
--- NP43.prj (project) ---

Proj Title=NP43
Current Plan=p01
Geom File=g01
Flow File=f01
Plan File=p01
DSS Export Rating Curves=0
DSS Export Rating Curve Sorted=0
DSS Export Volume Flow Curves=0
DXF OffsetX=0
DXF OffsetY=0
DXF ScaleX=0
DXF ScaleY=0

--- NP43.p01 (plan) ---

Plan Title=Floodplain
Program Version=4.00
Geom File=g01
Flow File=f01
K Sum by GR=0
Std Step Tol=0.01
Critical Tol=0.01
Num of Std Step Trials=20
Max Error Tol=0.3
Flow Tol Ratio=0.001
Split Flow NTrial=30
Split Flow Tol=0.02
Split Flow Ratio=0.02
Log Output Level=0
Friction Slope Method=1
Unsteady Friction Slope Method=2
Unsteady Bridges Friction Slope Method=1
Global Log Level=0
CheckData=False
Run HTab=0
Run UNet=0
Run PostProcess=0
UNET Theta=0
UNET Theta Warmup=0
UNET ZTol=0
UNET ZSATol=0
UNET MxIter=0
UNET MaxInSteps=0
UNET DtIC=0
UNET DtMin=0
UNET MaxCRTS=0
UNET WFStab=0
UNET SFStab=0
UNET WFX=0
UNET SFX=0
UNET DSS MLevel=0
UNET DZMax Abort=0
UNET Convert EG Bridges=0
UNET Use Existing IB Tables=0
UNET Froude Limit=0
UNET Froude Power=0
Write IC File=0
Echo Input=False
Echo Output=False
Write Detailed=0

--- NP43.f01 (steady flow) ---

Flow Title=NFF Regression Equation
Program Version=4.00
Number of Profiles=1
Profile Names=P100yr
River Rch & RM=NP43,Main      ,2669.6
324.2093
River Rch & RM=NP43,Main      ,2075.7
518.5751
Boundary for River Rch & Prof#=NP43,Main      ,1
Up Type=0
Dn Type=3
Dn Slope=0.037294

--- NP43.g01 (geometry) ---

Geom Title=USGS 3m DEM
Program Version=4.00

River Reach=NP43     ,Main
Reach XY= 30
     1963095.662      395181.609     1963041.464      395151.745
     1962979.582      395128.448     1962911.327      395114.612
     1962805.228      395100.873     1962610.950      395055.909
     1962573.621      395055.909     1962544.151      395057.790
     1962533.263      395062.055     1962411.634      395157.303
     1962370.853      395194.834     1962319.992      395217.599
     1962196.942      395237.462     1962135.010      395242.552
     1962018.435      395231.956     1961927.259      395228.484
     1961800.523      395228.484     1961749.012      395235.842
     1961680.731      395266.678     1961602.607      395294.456
     1961524.481      395330.914     1961364.759      395417.720
     1961305.731      395473.275     1961244.968      395518.414
     1961178.996      395577.442     1961116.139      395638.777
     1961079.414      395695.890     1961050.280      395720.454
     1960918.579      395766.678     1960668.858      395789.719

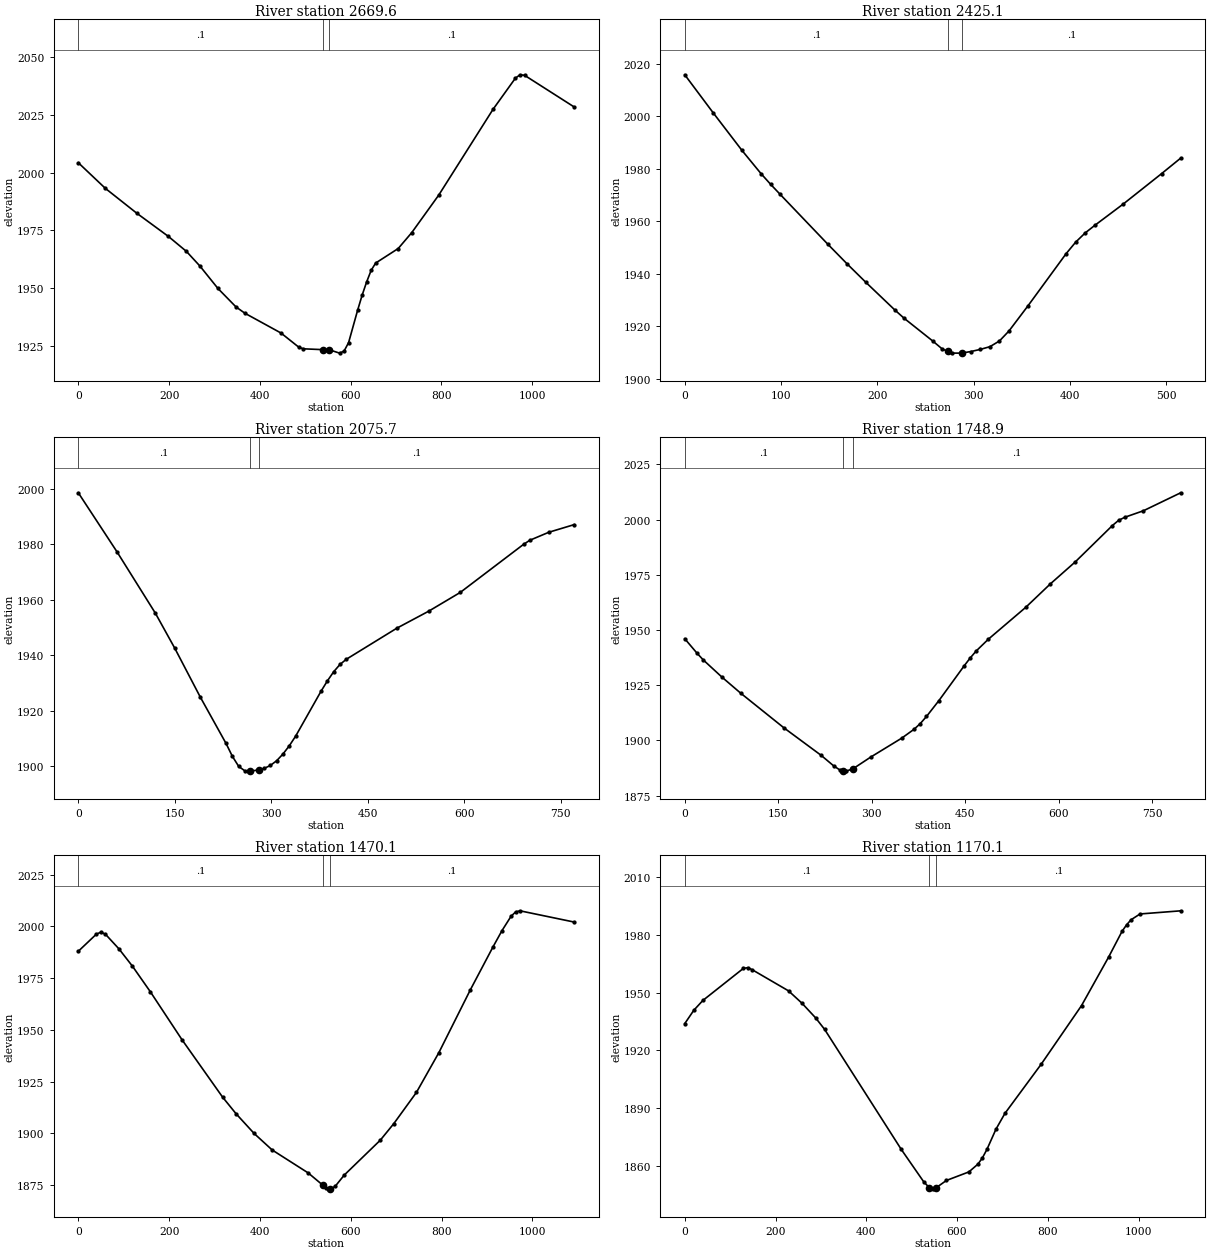
Type RM Length L Ch R = 1 ,2669.6,252.3,244.5,237.8
XS GIS Cut Line= 3
     1963350.333      394698.708     1963086.904      395176.783
     1962847.683      395668.543
#Sta/Elev= 30
       0 2004.22    59.6 1993.16   129.0 1982.41   198.5 1972.42   238.2 1965.97
   268.0 1959.63   307.7 1949.96   347.4 1942.01   367.2 1939.26   446.6 1930.74
   486.3 1924.55   496.2 1923.92   538.3 1923.57   553.3 1923.49   575.7 1922.06
   585.6 1922.92   595.6 1926.60   615.4 1940.51   625.4 1947.04   635.3 1952.75
   645.3 1957.77   655.2 1960.93   704.9 1967.20   734.8 1974.07   794.4 1990.30
   913.7 2027.22   963.4 2040.78   973.4 2042.17   983.3 2041.98  1092.7 2028.30
#Mann= 3 , 0 , 0
       0     0.1       0   538.3   0.045       0   553.3     0.1       0
Bank Sta=   538.3,   553.3
Exp/Cntr=0.3,0.1

Type RM Length L Ch R = 1 ,2425.1,362.2,349.5,336.8
XS GIS Cut Line= 2
     1962899.246      394828.900     1962818.807      395337.675
#Sta/Elev= 30
       0 2015.87    29.7 2001.29    59.4 1987.06    79.2 1978.20    89.2 1974.12
    99.1 1970.29   148.6 1951.30   168.4 1943.89   188.2 1936.74   217.9 1926.34
   227.8 1923.09   257.6 1914.40   267.4 1911.39   273.4 1910.44   277.4 1909.80
   287.3 1909.79   288.4 1909.86   297.2 1910.40   307.1 1911.22   317.0 1912.25
   326.9 1914.43   336.8 1918.24   356.6 1927.86   396.2 1947.73   406.1 1952.11
   416.0 1955.62   425.9 1958.48   455.7 1966.68   495.3 1978.20   515.1 1984.10
#Mann= 3 , 0 , 0
       0     0.1       0   273.4   0.045       0   288.4     0.1       0
Bank Sta=   273.4,   288.4
Exp/Cntr=0.3,0.1

Type RM Length L Ch R = 1 ,2075.7,318.3,326.4,334.5
XS GIS Cut Line= 3
     1962513.140      394804.769     1962499.064      395034.019
     1962714.237      395530.728
#Sta/Elev= 30
       0 1998.59    59.9 1977.41   119.8 1955.21   149.8 1942.66   189.7 1924.96
   229.7 1908.27   239.5 1903.65   249.4 1899.99   259.2 1898.36   266.6 1898.31
   269.0 1898.30   281.6 1898.82   288.7 1899.25   298.6 1900.34   308.4 1902.05
   318.3 1904.49   328.1 1907.45   337.9 1910.90   377.3 1927.05   387.2 1930.79
   397.0 1934.09   406.8 1936.73   416.7 1938.61   495.4 1949.83   544.6 1955.91
   593.8 1962.68   692.3 1980.02   702.1 1981.50   731.6 1984.38   771.0 1987.13
#Mann= 3 , 0 , 0
       0     0.1       0   266.6   0.045       0   281.6     0.1       0
Bank Sta=   266.6,   281.6
Exp/Cntr=0.3,0.1

Type RM Length L Ch R = 1 ,1748.9,276.1,278.3,280.6
XS GIS Cut Line= 2
     1962227.583      394969.668     1962263.780      395764.000
#Sta/Elev= 30
       0 1946.03    19.9 1939.41    29.8 1936.41    59.6 1928.67    89.5 1921.44
   159.0 1905.71   218.7 1893.26   238.6 1888.54   248.5 1886.68   254.3 1886.35
   258.4 1886.12   269.3 1887.10   298.2 1892.48   347.9 1901.05   367.8 1905.09
   377.7 1907.66   387.6 1910.85   407.5 1918.03   447.3 1933.49   457.2 1937.16
   467.2 1940.47   487.0 1945.88   546.7 1960.24   586.4 1970.91   626.2 1980.83
   685.8 1997.30   695.8 1999.66   705.7 2001.04   735.5 2003.98   795.2 2012.10
#Mann= 3 , 0 , 0
       0     0.1       0   254.3   0.045       0   269.3     0.1       0
Bank Sta=   254.3,   269.3
Exp/Cntr=0.3,0.1

Type RM Length L Ch R = 1 ,1470.1,310,300,291.4
XS GIS Cut Line= 3
     1961992.689      394685.277     1961962.404      395230.436
     1961932.991      395775.644
#Sta/Elev= 30
       0 1987.98    39.7 1996.24    49.6 1997.20    59.6 1996.24    89.4 1989.14
   119.1 1980.78   158.8 1968.33   228.3 1945.21   317.7 1917.46   347.4 1909.42
   387.2 1899.88   426.9 1891.91   506.3 1880.80   538.5 1874.89   546.0 1873.49
   553.5 1873.10   555.9 1872.98   565.8 1874.37   585.7 1879.78   665.1 1896.65
   694.9 1904.68   744.6 1919.73   794.2 1939.03   863.7 1969.47   913.3 1990.10
   933.2 1998.00   953.0 2004.88   963.0 2006.98   972.9 2007.52  1092.0 2002.09
#Mann= 3 , 0 , 0
       0     0.1       0   538.5   0.045       0   553.5     0.1       0
Bank Sta=   538.5,   553.5
Exp/Cntr=0.3,0.1

Type RM Length L Ch R = 1 ,1170.1,302.6,300,294.3
XS GIS Cut Line= 3
     1961463.254      394764.395     1961670.432      395270.340
     1961845.363      395787.506
#Sta/Elev= 30
       0 1933.95    19.9 1940.86    39.8 1945.95   129.2 1962.64   139.2 1962.99
   149.1 1961.85   228.6 1950.94   258.4 1944.48   288.3 1936.90   308.2 1930.89
   477.1 1868.51   526.8 1851.60   539.2 1848.58   546.7 1847.88   554.2 1848.65
   576.5 1852.38   626.1 1856.83   646.0 1860.87   655.9 1864.14   665.8 1868.50
   685.7 1879.01   705.5 1887.25   785.0 1912.67   874.3 1943.28   933.8 1968.41
   963.6 1981.87   973.6 1985.26   983.5 1987.90  1003.3 1990.91  1092.7 1992.54
#Mann= 3 , 0 , 0
       0     0.1       0   539.2   0.045       0   554.2     0.1       0
Bank Sta=   539.2,   554.2
Exp/Cntr=0.3,0.1

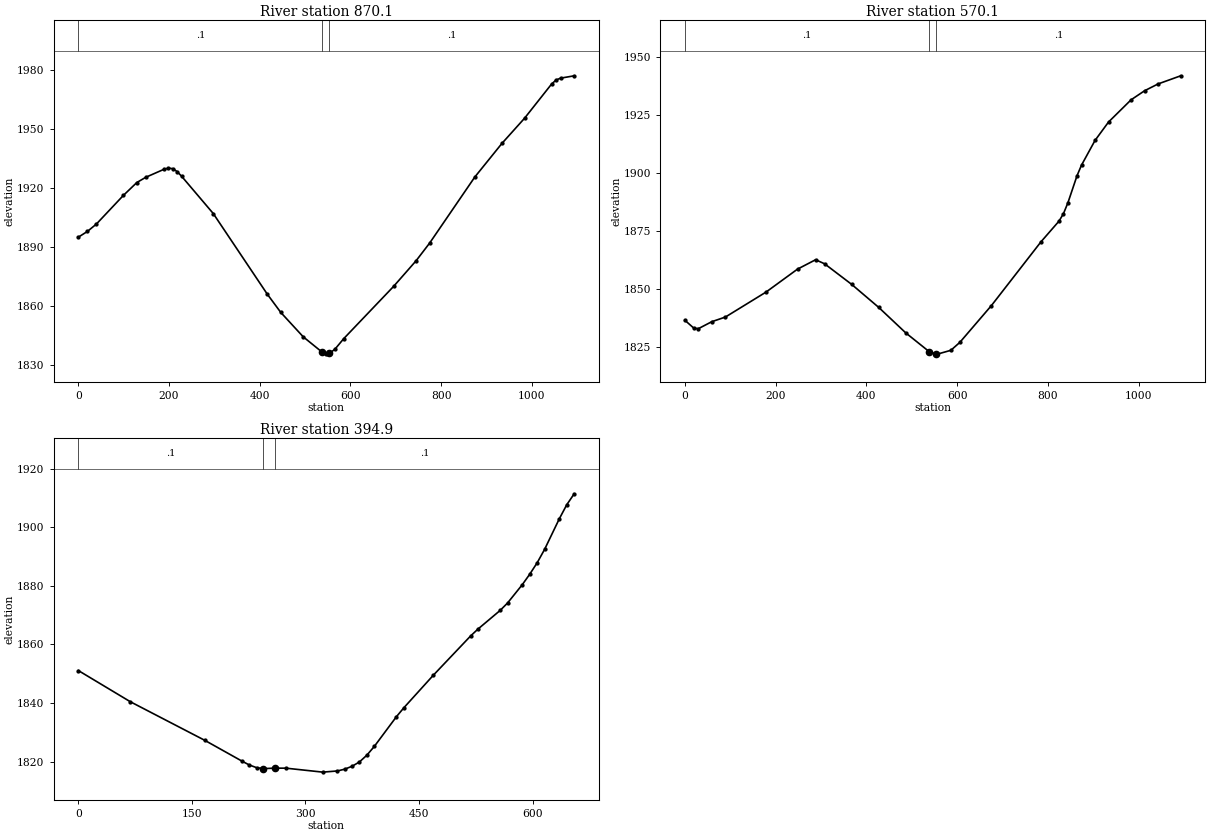
Type RM Length L Ch R = 1 ,870.1,305.2,300,295.5
XS GIS Cut Line= 3
     1961136.439      394920.499     1961399.783      395398.421
     1961698.713      395857.531
#Sta/Elev= 30
       0 1894.95    19.8 1897.84    39.7 1901.61    99.2 1916.21   129.0 1922.81
   148.8 1925.49   188.5 1929.52   198.4 1930.15   208.4 1929.88   218.3 1928.32
   228.2 1925.89   297.6 1906.99   416.7 1865.89   446.5 1856.57   496.1 1844.11
   538.2 1836.22   545.7 1835.31   553.2 1835.65   565.6 1837.74   585.5 1843.25
   695.1 1869.80   744.9 1882.92   774.8 1891.94   874.4 1925.62   934.2 1942.75
   984.0 1955.57  1043.7 1973.02  1053.7 1975.10  1063.6 1976.04  1093.5 1977.22
#Mann= 3 , 0 , 0
       0     0.1       0   538.2   0.045       0   553.2     0.1       0
Bank Sta=   538.2,   553.2
Exp/Cntr=0.3,0.1

Type RM Length L Ch R = 1 ,570.1,175.4,175.2,176
XS GIS Cut Line= 3
     1960802.798      395181.781     1961168.579      395587.859
     1961551.171      395977.300
#Sta/Elev= 30
       0 1836.66    19.9 1833.24    29.8 1833.01    59.6 1836.03    89.4 1838.01
   178.9 1848.74   248.4 1858.63   288.2 1862.66   308.0 1860.92   367.7 1852.06
   427.3 1842.16   486.9 1831.20     539 1823.06     554 1822.11   556.5 1822.07
   586.2 1823.71   606.1 1827.14   675.6 1842.95   784.8 1870.37   824.5 1879.26
   834.4 1882.49   844.3 1887.24   864.2 1898.78   874.1 1903.34   903.9 1913.97
   933.6 1921.87   983.3 1931.43  1013.0 1935.32  1042.8 1938.26  1092.5 1941.75
#Mann= 3 , 0 , 0
       0     0.1       0     539   0.045       0     554     0.1       0
Bank Sta=     539,     554
Exp/Cntr=0.3,0.1

Type RM Length L Ch R = 1 ,394.9,380.1,394.9,409.6
XS GIS Cut Line= 4
     1960992.849      395478.443     1961029.026      395691.454
     1961133.870      395805.999     1961405.097      395888.680
#Sta/Elev= 30
       0 1851.09    68.8 1840.43   167.0 1827.28   216.1 1820.19   225.8 1818.87
   235.5 1817.95   244.5 1817.63   259.5 1817.79   274.3 1817.78   322.8 1816.43
   342.2 1816.83   351.9 1817.44   361.6 1818.44   371.3 1819.90   381.1 1822.21
   390.9 1825.19   420.2 1835.36   430.0 1838.40   469.1 1849.55   518.0 1862.85
   527.8 1865.23   557.1 1871.59   566.9 1874.12   586.4 1880.39   596.2 1883.94
   606.0 1887.84   615.8 1892.40   635.3 1902.87   645.1 1907.64   654.9 1911.38
#Mann= 3 , 0 , 0
       0     0.1       0   244.5   0.045       0   259.5     0.1       0
Bank Sta=   244.5,   259.5
Exp/Cntr=0.3,0.1